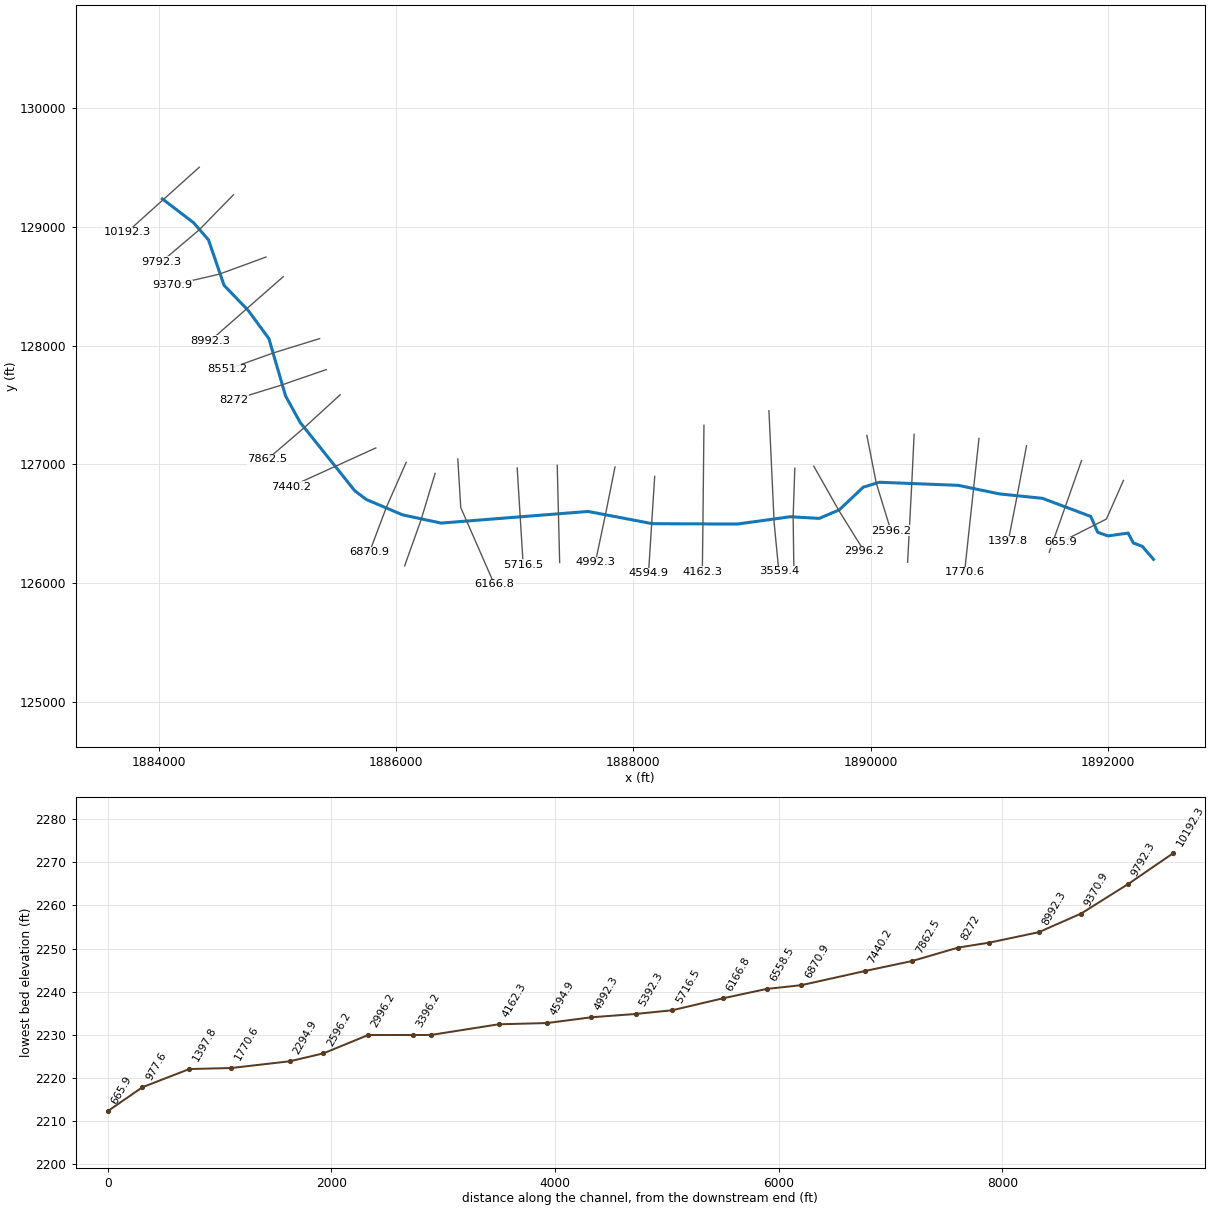
--- FlppngCrk.prj (project) ---

Proj Title=FlppngCrk
Current Plan=p01
Default Exp/Contr=0,0
English Units
Geom File=g01
Flow File=f01
Plan File=p01
BEGIN DESCRIPTION:
END DESCRIPTION:
DSS Export Rating Curves= 0
DSS Export Rating Curve Sorted= 0
DSS Export Volume Flow Curves= 0
DXF OffsetX= 0
DXF OffsetY= 0
DXF ScaleX= 0
DXF ScaleY= 0

--- FlppngCrk.p01 (plan) ---

Plan Title=Floodplain
Program Version=4.00
Geom File=g01
Flow File=f01
K Sum by GR=0
Std Step Tol=0.01
Critical Tol=0.01
Num of Std Step Trials=20
Max Error Tol=0.3
Flow Tol Ratio=0.001
Split Flow NTrial=30
Split Flow Tol=0.02
Split Flow Ratio=0.02
Log Output Level=0
Friction Slope Method=1
Unsteady Friction Slope Method=2
Unsteady Bridges Friction Slope Method=1
Global Log Level=0
CheckData=False
Run HTab=0
Run UNet=0
Run PostProcess=0
UNET Theta=0
UNET Theta Warmup=0
UNET ZTol=0
UNET ZSATol=0
UNET MxIter=0
UNET MaxInSteps=0
UNET DtIC=0
UNET DtMin=0
UNET MaxCRTS=0
UNET WFStab=0
UNET SFStab=0
UNET WFX=0
UNET SFX=0
UNET DSS MLevel=0
UNET DZMax Abort=0
UNET Convert EG Bridges=0
UNET Use Existing IB Tables=0
UNET Froude Limit=0
UNET Froude Power=0
Write IC File=0
Echo Input=False
Echo Output=False
Write Detailed=0

--- FlppngCrk.f01 (steady flow) ---

Flow Title=NFF Regression Equation
Program Version=4.00
Number of Profiles=1
Profile Names=P100yr
River Rch & RM=FlppngCrk,Main      ,10192.3
667.1486
River Rch & RM=FlppngCrk,Main      ,9370.9
690.3383
River Rch & RM=FlppngCrk,Main      ,5716.5
760.6633
River Rch & RM=FlppngCrk,Main      ,3559.4
840.4063
River Rch & RM=FlppngCrk,Main      ,665.9
916.5055
Boundary for River Rch & Prof#=FlppngCrk,Main      ,1
Up Type=0
Dn Type=3
Dn Slope=0.009456

--- FlppngCrk.g01 (geometry) ---

Geom Title=USGS 3m DEM
Program Version=4.10

River Reach=FlppngCrk       ,Main
Reach XY= 30
      1884028.79      129236.868     1884292.216      129035.867
     1884417.806      128891.423     1884549.405       128508.31
     1884751.935      128298.058     1884927.217      128059.322
     1885067.639      127576.628     1885190.397      127354.056
     1885649.665      126779.143     1885747.322      126704.924
     1886054.613      126574.716     1886378.832      126505.706
      1887617.48       126603.68     1888159.227      126500.757
     1888875.685      126497.441      1889321.54      126559.091
     1889566.145       126545.15     1889734.442      126616.635
     1889937.159      126808.014     1890073.351      126849.614
     1890737.375       126823.67      1891084.23      126751.631
     1891447.821      126714.183     1891855.142      126561.506
     1891913.476      126428.333     1891999.332      126397.513
     1892169.943      126421.729     1892213.972      126338.074
     1892289.281      126309.751     1892384.123      126200.097

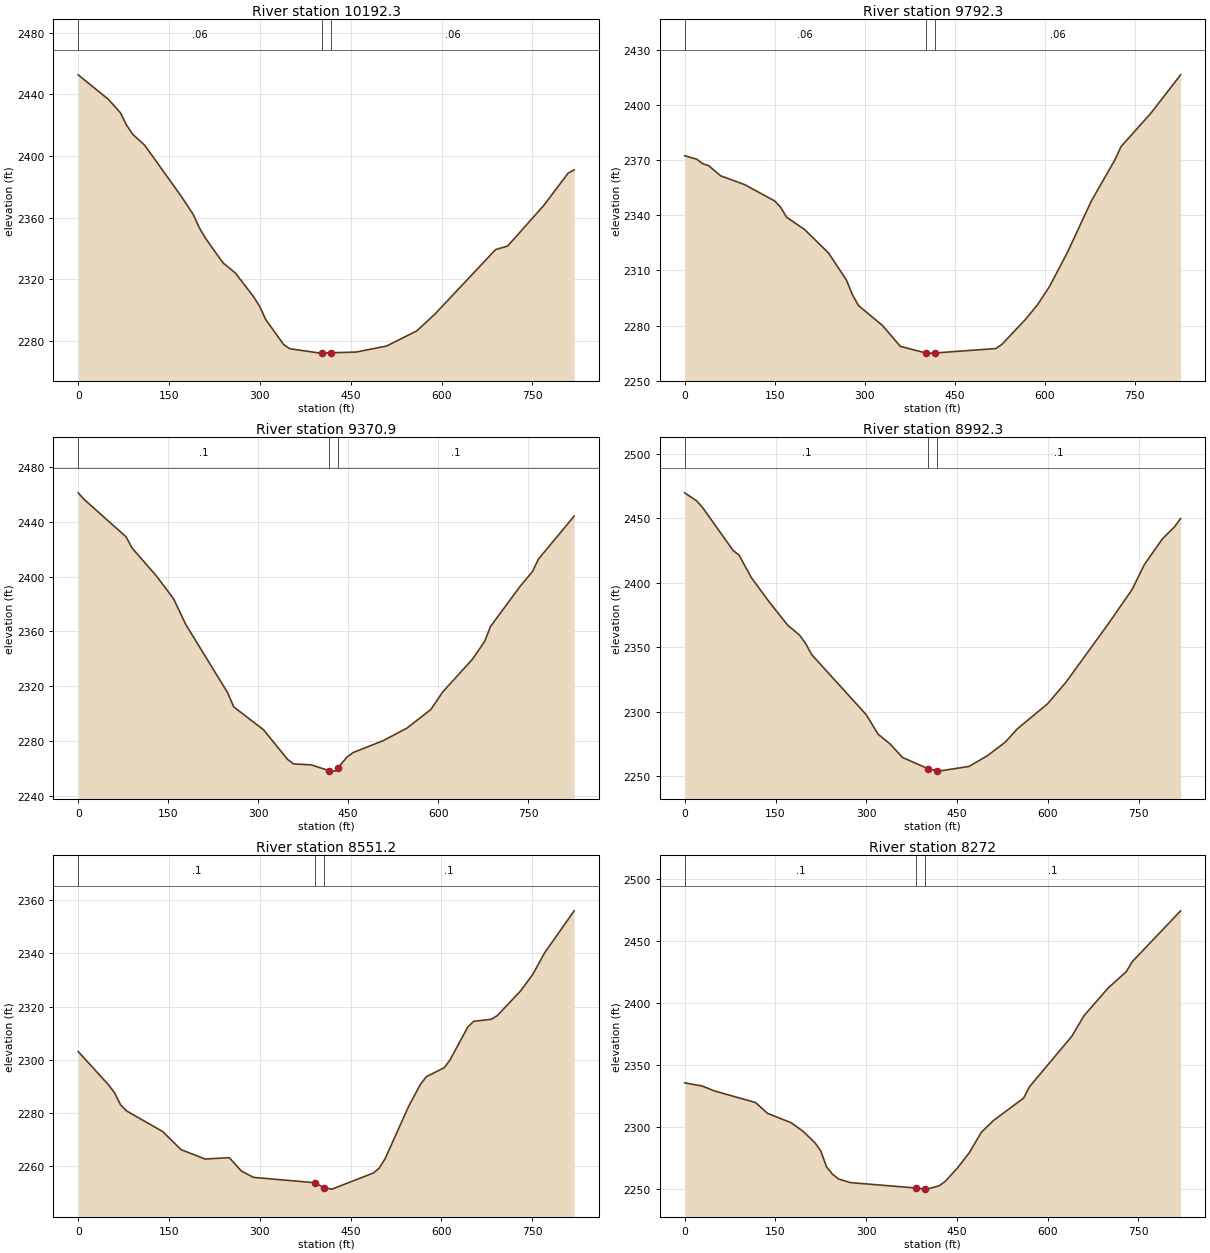
Type RM Length L Ch R = 1 ,10192.3 ,398.6,399.9,399.2
XS GIS Cut Line= 3
     1884340.054      129503.147     1884035.474       129229.43
     1883730.894      128955.713
#Sta/Elev= 30
       0 2452.57    49.9 2436.66    69.9 2427.89    79.9 2419.92    89.9 2414.07
   109.9 2406.87   169.8 2374.02   189.8 2362.14   199.8 2353.54   209.7 2346.92
   229.7 2335.75   239.7 2330.46   259.7    2324   289.6 2308.66   299.6 2302.51
   309.6 2293.93   339.6  2277.5   349.6 2274.95   399.5  2272.1     402 2272.14
     417  2272.3   459.4 2272.82   509.4 2276.73   559.3 2286.56   589.3  2297.5
   689.2 2339.24   709.1 2341.51   769.1 2367.99     809 2388.81     819 2390.92
#Mann= 3 , 0 , 0
       0     .06       0     402    .045       0     417     .06       0
Bank Sta=402,417
XS Rating Curve= 0 ,0
Exp/Cntr=0.3,0.1

Type RM Length L Ch R = 1 ,9792.3  ,432.1,421.1,410.2
XS GIS Cut Line= 3
     1884628.011      129271.189     1884342.077      128978.054
     1884023.749      128708.678
#Sta/Elev= 30
       0 2372.54      20 2370.65      30 2368.19      40 2367.11    59.9 2361.59
    99.9 2356.79   149.8 2347.92   159.8 2344.55   169.8 2339.04   199.8 2332.33
   239.7 2319.56   269.7 2304.71   279.7 2296.76   289.6  2290.9   329.6 2280.06
   359.6 2268.63     402 2265.06   409.5 2264.98     417 2265.05   518.7 2267.49
   528.6 2269.73   568.4 2283.51   588.2 2291.44   608.1 2301.33   637.9 2319.87
   677.6 2347.78   717.3 2370.49   727.2 2377.51   776.9 2395.68   826.5  2416.6
#Mann= 3 , 0 , 0
       0     .06       0     402    .045       0     417     .06       0
Bank Sta=402,417
XS Rating Curve= 0 ,0
Exp/Cntr=0.3,0.1

Type RM Length L Ch R = 1 ,9370.9  ,369.5,378.6,389.7
XS GIS Cut Line= 3
      1884902.97      128746.947     1884509.843      128602.912
     1884112.256      128510.207
#Sta/Elev= 30
       0    2461      10 2456.15    79.8 2428.92    89.7 2420.84   129.6 2400.82
   149.5 2389.37   159.5 2383.33   179.4    2365   249.2 2315.26   259.2    2305
     309 2288.27   348.9 2266.79   358.9 2263.39   388.8 2262.67   417.5 2258.55
   428.6 2258.12   432.5 2260.27   448.6 2268.57   458.5  2271.7   508.3 2280.29
   548.1 2289.47     588 2303.04   607.9 2315.91   657.7 2339.91   677.6 2352.66
   687.5 2363.59   737.3 2393.12   757.2 2403.45   767.2  2412.6   826.9 2444.01
#Mann= 3 , 0 , 0
       0      .1       0   417.5    .045       0   432.5      .1       0
Bank Sta=417.5,432.5
XS Rating Curve= 0 ,0
Exp/Cntr=0.3,0.1

Type RM Length L Ch R = 1 ,8992.3  ,450.6,441.1,432.2
XS GIS Cut Line= 3
     1885048.177      128581.331     1884740.278      128311.353
     1884432.379      128041.374
#Sta/Elev= 30
       0 2469.93      20 2463.65      30 2458.23    79.9 2425.23    89.9 2421.52
   109.9  2404.2   139.8 2385.06   169.8 2367.32   189.8 2359.35   199.8 2352.92
   209.7 2344.33   299.6 2297.73   319.6  2282.4   339.6 2274.77   359.6 2264.44
     402 2255.67     417  2253.9   419.5 2253.79   469.4 2257.43   499.4  2265.6
   529.4 2276.28   549.3 2286.62   599.3 2306.09   629.2 2322.56   699.2 2367.91
   739.1    2395   759.1 2414.18     789 2434.22     809 2443.59     819 2449.98
#Mann= 3 , 0 , 0
       0      .1       0     402    .045       0     417      .1       0
Bank Sta=402,417
XS Rating Curve= 0 ,0
Exp/Cntr=0.3,0.1

Type RM Length L Ch R = 1 ,8551.2  ,278.3,279,279.1
XS GIS Cut Line= 3
     1885354.584      128059.565     1884963.401      127938.771
     1884577.568       127800.03
#Sta/Elev= 30
       0 2303.11    49.9 2290.65    59.9 2287.67    69.9 2283.08    79.9 2280.79
   139.8 2272.99   169.8 2266.23   209.7 2262.69   249.6 2263.21   269.6 2258.17
   289.6 2255.79   390.8 2253.78   405.8 2251.91   419.2 2251.37   487.5 2257.41
   497.3 2259.25     507 2262.79   546.1 2282.57   565.6 2290.85   575.4 2293.68
   604.7 2297.03   614.4 2299.99   643.7 2312.35   653.5  2314.5   682.8 2315.25
   692.5 2316.66   731.6  2326.1   751.1 2332.16   770.6 2340.24   819.4 2356.04
#Mann= 3 , 0 , 0
       0      .1       0   390.8    .045       0   405.8      .1       0
Bank Sta=390.8,405.8
XS Rating Curve= 0 ,0
Exp/Cntr=0.3,0.1

Type RM Length L Ch R = 1 ,8272    ,400.2,409.5,418.4
XS GIS Cut Line= 3
      1885410.63      127798.522     1885022.545      127664.825
     1884631.359      127544.308
#Sta/Elev= 30
       0 2335.77    29.3 2333.15    48.9  2329.3   117.3 2319.89   136.8 2311.27
   175.9 2303.68   195.5 2296.85     215 2287.75   224.8 2281.14   234.6 2268.14
   244.3 2262.26   254.1 2258.44   273.6  2255.5   382.8 2251.09   397.8 2250.31
   400.7 2250.22   420.4 2252.86   430.4 2256.34   450.4 2266.92   470.4 2279.46
   490.3  2295.9   510.3  2305.4   560.2  2323.5   570.2 2332.76   640.1 2373.37
   660.1 2389.82     700 2412.11     730 2425.28   739.9 2433.33   819.8 2474.25
#Mann= 3 , 0 , 0
       0      .1       0   382.8    .045       0   397.8      .1       0
Bank Sta=382.8,397.8
XS Rating Curve= 0 ,0
Exp/Cntr=0.3,0.1

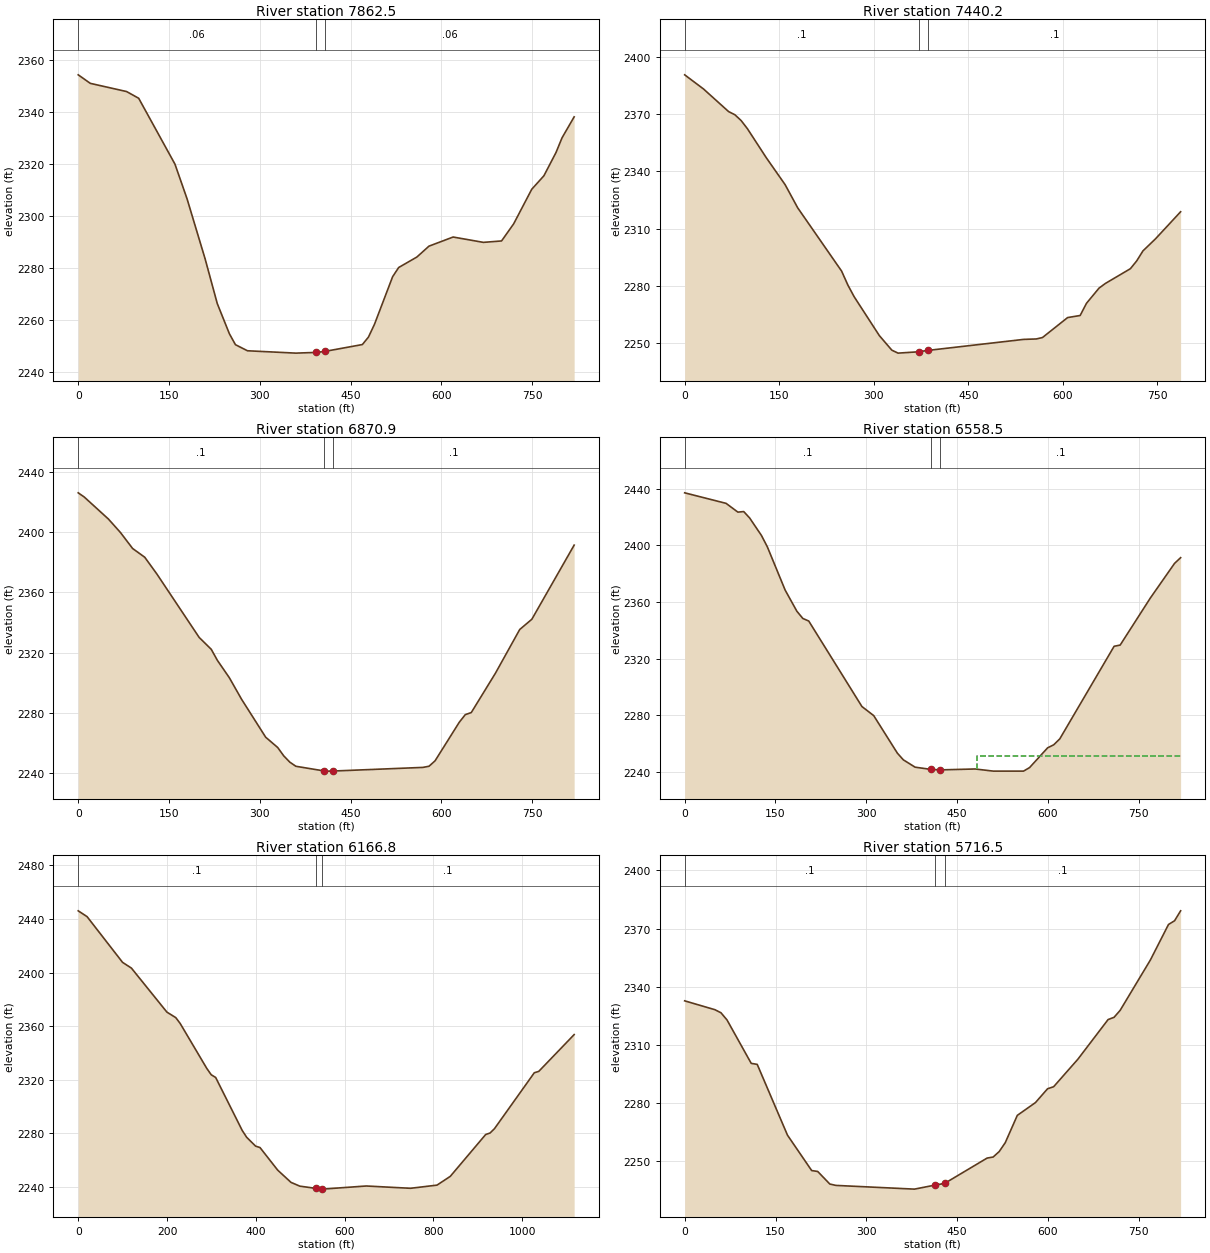
Type RM Length L Ch R = 1 ,7862.5  ,429.4,422.3,415.7
XS GIS Cut Line= 3
     1885527.666      127586.303     1885225.476      127310.014
     1884914.471      127043.237
#Sta/Elev= 30
       0 2354.45      20 2351.16    79.9    2348    99.9 2345.41   159.8 2320.01
   179.8 2306.63   209.7 2283.41   229.7 2266.23   249.7  2254.6   259.7 2250.37
   279.6 2248.02   359.5 2247.11   392.6 2247.38   407.6 2247.78   469.4 2250.42
   479.4 2253.28   489.4 2258.24   519.4 2276.61   529.4 2280.14   559.4 2284.17
   579.4 2288.37   619.3 2291.89   669.3 2289.83   699.3 2290.38   719.3 2296.98
   749.2 2310.33   769.2  2315.5   789.2 2324.47   799.2 2330.16   819.2 2338.24
#Mann= 3 , 0 , 0
       0     .06       0   392.6    .045       0   407.6     .06       0
Bank Sta=392.6,407.6
XS Rating Curve= 0 ,0
Exp/Cntr=0.3,0.1

Type RM Length L Ch R = 1 ,7440.2  ,552.5,569.3,587.1
XS GIS Cut Line= 2
      1885828.04      127138.508     1885111.651      126812.997
#Sta/Elev= 30
       0 2390.46    29.9 2383.05    69.7 2371.22    79.7 2369.55    89.6 2366.52
    99.6 2362.23   129.5 2347.06   159.4 2332.95   179.3 2320.86     249 2287.72
     259 2280.38   268.9 2274.31   308.8 2253.99   328.7 2246.33   338.6 2244.78
   371.1 2245.48   386.1 2246.21   537.9 2251.97   557.8 2252.19   567.7 2252.94
   607.6 2263.39   627.5 2264.48   637.5 2270.84   657.4 2278.79   667.4 2281.23
   707.2 2288.97   717.2 2293.05   727.1 2298.28     747 2304.59   786.9 2318.78
#Mann= 3 , 0 , 0
       0      .1       0   371.1    .045       0   386.1      .1       0
Bank Sta=371.1,386.1
XS Rating Curve= 0 ,0
Exp/Cntr=0.3,0.1

Type RM Length L Ch R = 1 ,6870.9  ,310.1,312.4,312.7
XS GIS Cut Line= 3
     1886084.218      127017.164     1885918.824      126642.488
     1885774.327      126259.035
#Sta/Elev= 30
       0 2426.03      10 2423.24      50 2408.61    69.9 2399.66    89.9 2389.11
   109.9 2383.32   129.9 2372.24   199.8 2330.15   219.8 2322.26   229.8 2315.02
   249.7 2303.41   269.7 2289.26   309.7 2263.99   329.6 2257.14   339.6 2251.58
   349.6 2247.44   359.6  2244.7   406.3 2241.61   409.6 2241.49   421.3 2241.55
   569.5 2243.96   579.5 2244.72   589.5 2248.31   629.4 2273.82   639.4 2278.92
   649.4 2280.35   689.4 2306.51   729.4 2335.41   749.4 2342.19   819.3 2391.35
#Mann= 3 , 0 , 0
       0      .1       0   406.3    .045       0   421.3      .1       0
Bank Sta=406.3,421.3
XS Rating Curve= 0 ,0
Exp/Cntr=0.3,0.1

Type RM Length L Ch R = 1 ,6558.5  ,375.1,391.6,409
XS GIS Cut Line= 3
     1886328.036      126923.681      1886209.11      126531.211
     1886071.416      126145.666
#Sta/Elev= 30
       0 2436.99    68.4 2429.56    87.9 2423.38    97.6 2423.76   107.4 2419.21
   126.9 2406.88   136.7 2398.78     166 2368.37   185.5 2353.36   195.3 2348.31
     205 2346.53   292.9 2286.18   312.4 2279.76   351.5 2253.27   361.3 2248.58
   380.8 2243.38   406.9 2241.83   421.9 2241.47     480 2242.11     510  2240.6
   559.9  2240.6   569.9 2243.09   599.8 2257.06   609.8 2259.17   619.8 2263.34
   709.6 2328.69   719.6 2329.55   769.6 2362.84   809.5 2387.21   819.5 2391.22
#Mann= 3 , 0 , 0
       0      .1       0   406.9    .045       0   421.9      .1       0
#XS Ineff= 2 , 0
                          482.22         2251.48
Permanent Ineff=
       F       F
Bank Sta=406.9,421.9
XS Rating Curve= 0 ,0
Exp/Cntr=0.3,0.1

Type RM Length L Ch R = 1 ,6166.8  ,458.6,450.4,442.1
XS GIS Cut Line= 3
     1886519.567      127045.589     1886544.093      126636.824
     1886828.168      125988.719
#Sta/Elev= 30
       0  2446.1      20 2441.75    99.9 2407.64   119.8 2403.37   199.8 2370.51
   219.7 2366.41   229.7 2362.03   289.6 2328.51   299.6 2323.77   309.6 2321.75
   369.6  2282.1   379.5 2277.09   399.5 2270.53   409.5 2269.43   449.4 2252.57
   479.3 2243.46   499.2 2240.64   534.9 2239.01     549 2238.42   549.9 2238.42
   648.7 2240.76   748.4 2239.04   808.2 2241.41   838.1 2247.95   917.8 2279.16
   927.8 2280.33   937.7 2283.56  1027.4 2325.28  1037.4 2326.28  1117.1 2353.73
#Mann= 3 , 0 , 0
       0      .1       0   534.9    .045       0   549.9      .1       0
Bank Sta=534.9,549.9
XS Rating Curve= 0 ,0
Exp/Cntr=0.3,0.1

Type RM Length L Ch R = 1 ,5716.5  ,325,324.2,323.3
XS GIS Cut Line= 3
     1887020.004      126969.784     1887045.285      126561.066
     1887070.566      126152.347
#Sta/Elev= 30
       0 2332.71    49.9 2328.15    59.9 2326.57    69.9 2322.87   109.9 2300.48
   119.8 2299.97   169.8 2263.46   209.7 2245.24   219.7 2244.76   239.7 2238.28
   249.7 2237.58   379.5 2235.66   414.2 2237.79   429.2  2238.6   499.4 2251.66
   509.4 2252.21   519.4 2255.02   529.4 2259.59   549.3 2273.67   579.3 2280.28
   599.3  2287.4   609.3 2288.44   649.2 2302.57   699.2 2323.05   709.1 2324.23
   719.1 2327.79   769.1 2353.78     799 2372.08     809 2373.98     819 2379.11
#Mann= 3 , 0 , 0
       0      .1       0   414.2    .045       0   429.2      .1       0
Bank Sta=414.2,429.2
XS Rating Curve= 0 ,0
Exp/Cntr=0.3,0.1

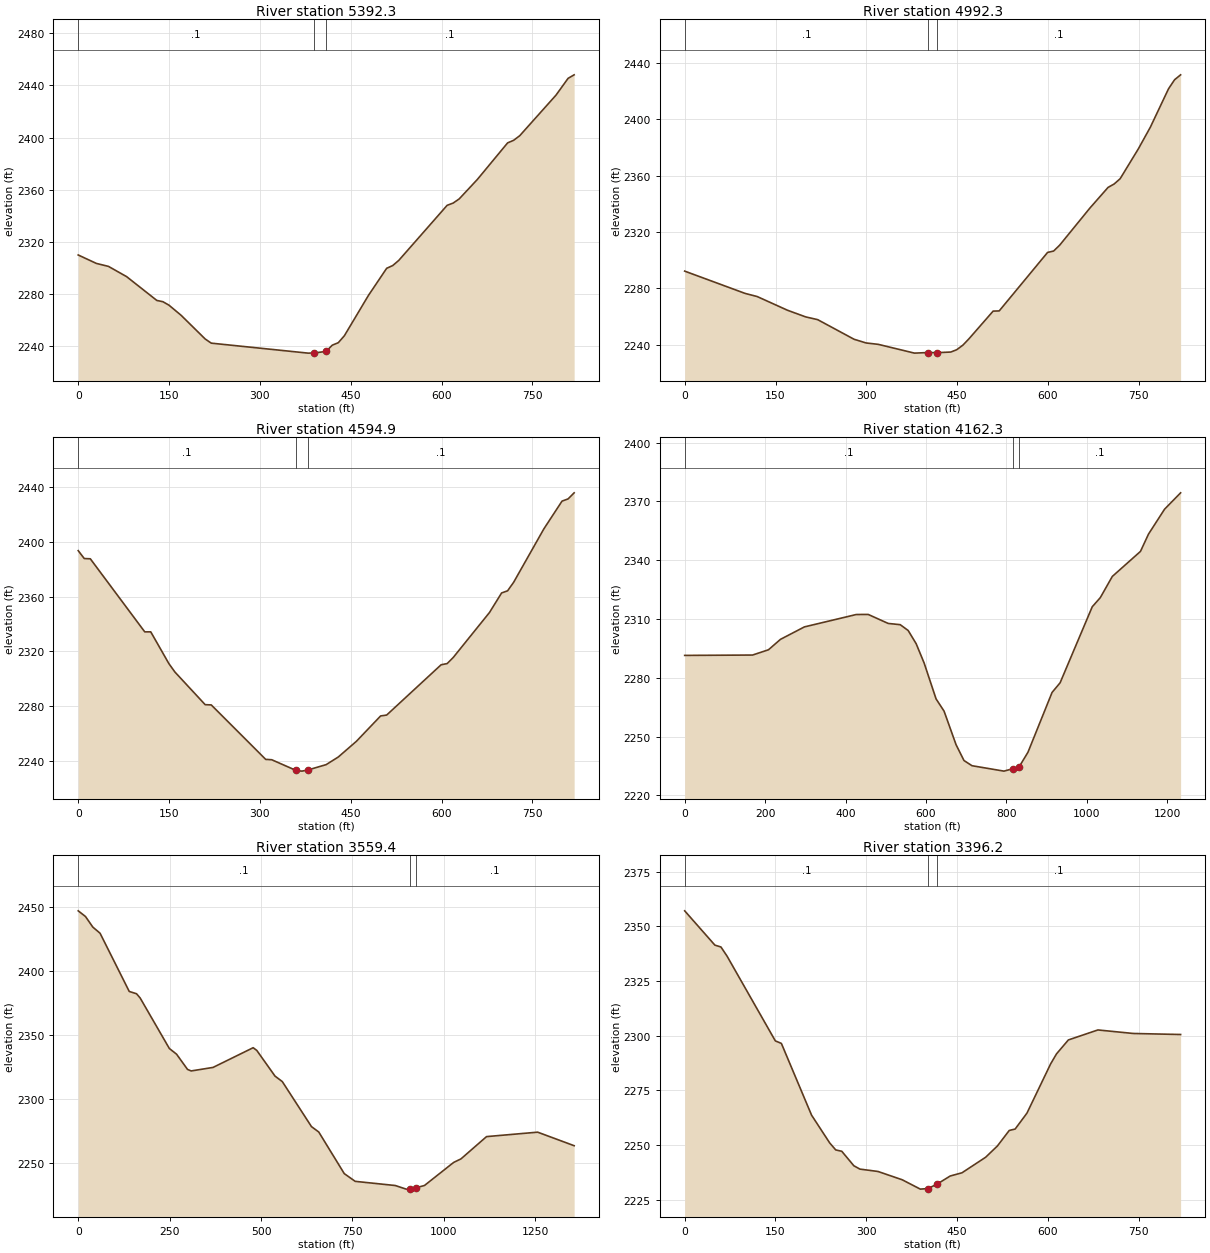
Type RM Length L Ch R = 1 ,5392.3  ,405,400,394.7
XS GIS Cut Line= 3
     1887357.661      126992.018     1887367.895      126582.646
     1887378.129      126173.274
#Sta/Elev= 30
       0 2310.05      30 2303.57    49.9 2301.31    79.9 2293.46   129.8  2275.2
   139.8 2274.23   149.8  2271.6   169.8 2263.86   209.7 2245.63   219.7 2242.45
   379.5  2234.8   389.5 2234.89   409.5 2236.15   419.5 2240.88   429.5  2242.8
   439.5  2248.1   479.4 2279.12   509.4 2299.84   519.4 2301.94   529.4  2305.9
   609.3 2348.14   619.2 2349.85   629.2 2353.05   659.2 2367.98   709.1 2395.98
   719.1 2397.98   729.1 2401.48     789 2432.58     809 2445.47     819 2448.17
#Mann= 3 , 0 , 0
       0      .1       0   389.5    .045       0   409.5      .1       0
Bank Sta=389.5,409.5
XS Rating Curve= 0 ,0
Exp/Cntr=0.3,0.1

Type RM Length L Ch R = 1 ,4992.3  ,394.2,397.4,400.8
XS GIS Cut Line= 3
     1887844.671      126978.538     1887764.223      126577.022
     1887679.506      126176.353
#Sta/Elev= 30
       0 2292.24    99.9  2276.4   119.8 2274.18   169.8 2264.46   199.8 2259.75
   219.7 2257.78   279.7 2243.87   299.6 2241.24   319.6 2240.26   379.5 2234.02
     402 2234.44     417 2234.35   439.5 2234.79   449.4 2236.48   459.4 2239.67
   469.4 2244.16   509.4 2263.85   519.4 2263.98   599.3 2305.51   609.3  2306.5
   619.2 2310.63   669.2 2337.01   699.2 2351.67   709.2 2354.09   719.1 2357.82
   749.1 2378.97   769.1  2394.5     799 2421.66     809 2428.09     819  2431.6
#Mann= 3 , 0 , 0
       0      .1       0     402    .045       0     417      .1       0
Bank Sta=402,417
XS Rating Curve= 0 ,0
Exp/Cntr=0.3,0.1

Type RM Length L Ch R = 1 ,4594.9  ,431.4,432.5,433.6
XS GIS Cut Line= 3
     1888179.143      126899.217     1888153.123      126490.544
     1888127.103      126081.872
#Sta/Elev= 30
       0 2393.47      10 2387.72      20 2387.53   109.9 2334.24   119.8 2334.25
   149.8 2311.04   159.8  2304.9   209.7 2281.14   219.7 2280.97   309.6 2241.25
   319.6 2240.98   359.6 2233.22   369.6 2232.68   379.5 2233.54   409.5 2237.43
   429.5 2242.98   459.4 2254.43   499.4 2272.92   509.4 2273.58   599.3 2310.24
   609.3 2311.12   619.2  2315.5   679.2 2348.37   699.2 2362.62   709.1 2364.19
   719.1 2370.42   769.1 2409.44     799  2429.6     809  2431.2     819 2435.64
#Mann= 3 , 0 , 0
       0      .1       0   359.6    .045       0   379.5      .1       0
Bank Sta=359.6,379.5
XS Rating Curve= 0 ,0
Exp/Cntr=0.3,0.1

Type RM Length L Ch R = 1 ,4162.3  ,601.5,602.7,604.1
XS GIS Cut Line= 3
     1888594.369      127329.555     1888585.884      126506.069
     1888580.795        126096.6
#Sta/Elev= 30
       0 2291.42   168.7  2291.6   208.4  2294.3   238.1  2299.6   297.7 2305.96
   426.6 2312.28   456.4 2312.31     506 2307.72   535.8  2307.1   555.6 2304.13
   575.5 2297.39   595.3 2287.55   625.1  2269.2   644.9 2262.99   674.7 2245.88
   694.5 2237.78   714.4 2235.15   793.8 2232.39   816.5 2233.65   831.5 2234.56
   853.5 2242.03   913.4 2272.53   933.4 2277.45  1013.3 2316.23  1033.3 2320.88
  1063.2  2331.7  1133.2 2344.47  1153.1 2353.27  1193.1    2366    1233 2374.35
#Mann= 3 , 0 , 0
       0      .1       0   816.5    .045       0   831.5      .1       0
Bank Sta=816.5,831.5
XS Rating Curve= 0 ,0
Exp/Cntr=0.3,0.1

Type RM Length L Ch R = 1 ,3559.4  ,165.1,163.2,162.5
XS GIS Cut Line= 3
     1889142.281      127452.182     1889186.266      126506.232
     1889225.798      126098.667
#Sta/Elev= 30
       0 2446.87    19.9 2442.44    39.9 2434.21    59.8 2429.39   139.6 2384.02
   159.5 2382.22   169.5 2378.89   249.2 2339.58   269.1 2335.08     299 2323.24
     309 2322.05   368.8  2324.8   478.5 2340.16   488.4 2338.05   538.3 2318.02
   558.2 2313.76     638 2278.64   657.9 2274.45   727.7    2242   757.6 2235.98
   867.2 2232.73   897.1 2229.92   908.2 2230.02   923.2 2230.93     947 2232.75
  1026.9 2250.75  1046.8 2253.48  1116.8 2270.86  1256.6 2274.32  1356.4 2263.77
#Mann= 3 , 0 , 0
       0      .1       0   908.2    .045       0   923.2      .1       0
Bank Sta=908.2,923.2
XS Rating Curve= 0 ,0
Exp/Cntr=0.3,0.1

Type RM Length L Ch R = 1 ,3396.2  ,387.3,399.8,412.2
XS GIS Cut Line= 3
      1889360.36      126967.394      1889346.25      126558.239
     1889351.874        126148.2
#Sta/Elev= 30
       0 2357.06    49.9 2341.39    59.9 2340.54    69.9 2336.42   149.8 2297.64
   159.8 2296.48   209.7 2263.69   239.6 2251.03   249.6 2247.82   259.6 2247.19
   279.6 2240.56   289.6 2239.05   319.5 2237.96   359.5 2234.17   389.4  2229.9
   401.9 2230.16   416.9 2232.16   438.7 2235.89   458.2 2237.36   497.3 2244.46
   516.8 2249.63   536.3  2256.7   546.1 2257.36   565.6 2264.63   604.7 2287.11
   614.4 2291.69     634 2298.06   682.8 2302.63   741.4 2301.02   819.5 2300.55
#Mann= 3 , 0 , 0
       0      .1       0   401.9    .045       0   416.9      .1       0
Bank Sta=401.9,416.9
XS Rating Curve= 0 ,0
Exp/Cntr=0.3,0.1

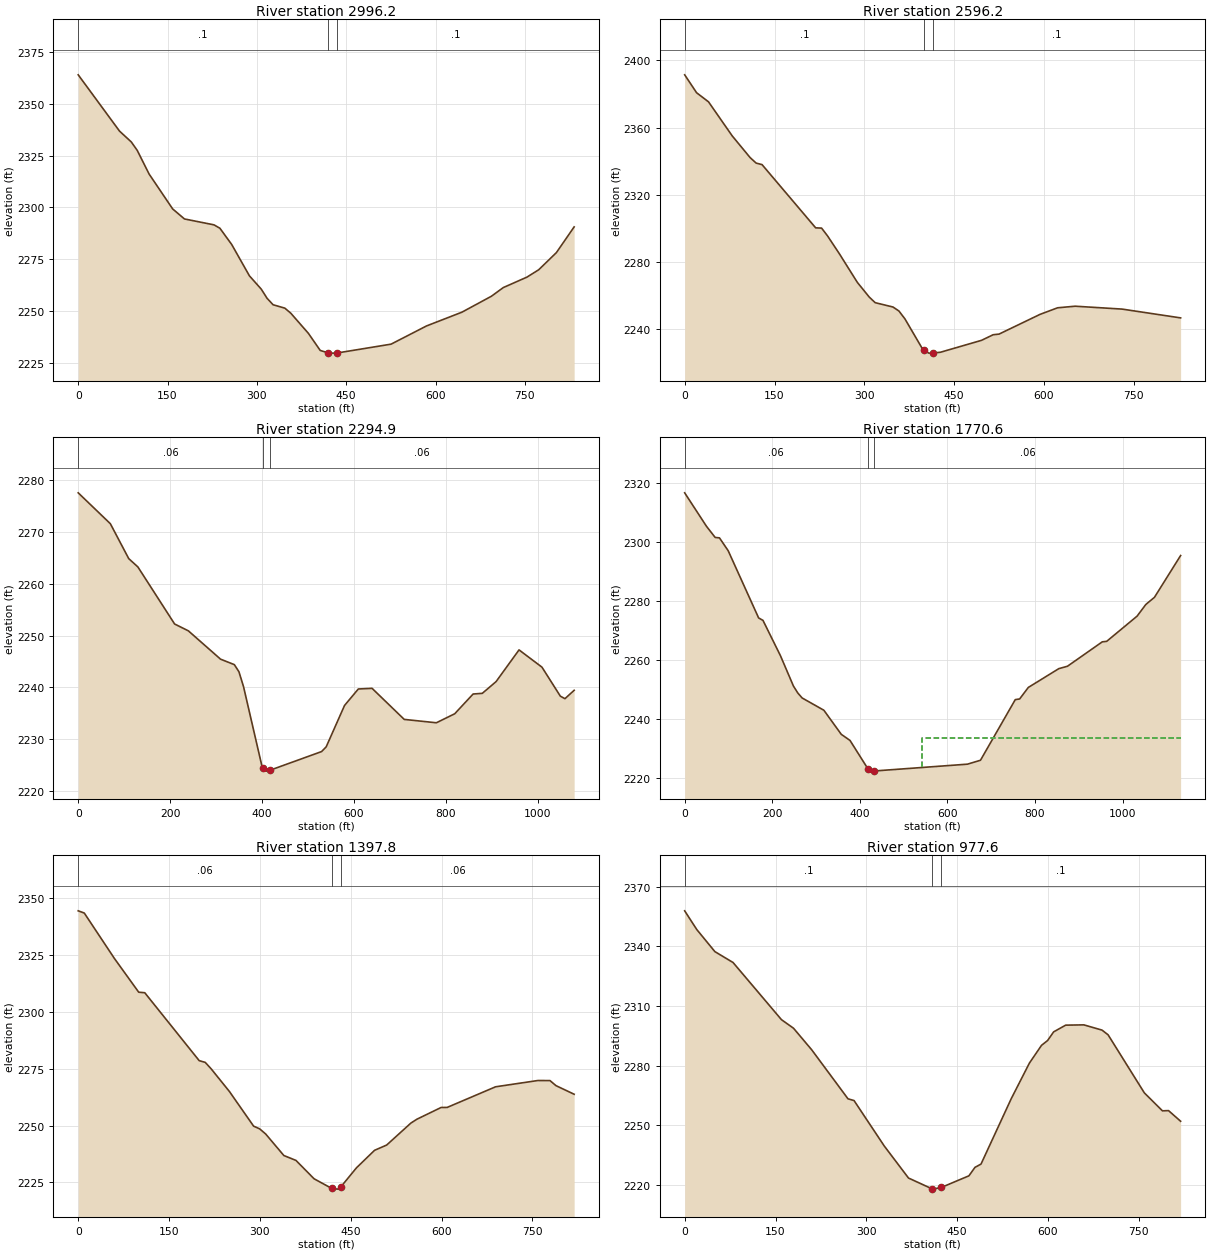
Type RM Length L Ch R = 1 ,2996.2  ,407,399.9,394.1
XS GIS Cut Line= 3
     1889520.047      126985.192     1889730.147      126614.283
     1889944.809      126269.079
#Sta/Elev= 30
       0 2363.83    69.4 2336.74    89.2 2331.51    99.1 2327.48     119 2316.11
   158.6  2299.3   178.4 2294.47     228 2291.63   237.9 2290.01   257.8 2282.16
   287.5  2267.1   307.3 2260.72   317.2 2256.27   327.2 2253.19     347 2251.54
   356.9 2249.14   386.6  2239.4   406.4 2231.19   418.8 2230.11   426.3  2229.9
   433.8 2229.92   525.4 2234.22   584.9 2242.98   644.4 2249.61     694  2257.3
   713.8 2261.45   753.5 2266.47   773.3 2270.02     803 2278.28   832.8 2290.65
#Mann= 3 , 0 , 0
       0      .1       0   418.8    .045       0   433.8      .1       0
Bank Sta=418.8,433.8
XS Rating Curve= 0 ,0
Exp/Cntr=0.3,0.1

Type RM Length L Ch R = 1 ,2596.2  ,306.8,301.2,293.3
XS GIS Cut Line= 3
     1889967.748      127244.191     1890046.577      126844.336
     1890170.214      126442.377
#Sta/Elev= 30
       0 2391.41    19.9 2380.74    39.8 2375.32    79.5 2354.98   109.3  2342.1
   119.3 2338.84   129.2 2337.92   218.7 2300.27   228.6 2300.12   238.6 2295.44
   258.4 2284.78   288.3 2267.79   308.2 2259.03   318.1 2255.69   347.9  2253.1
   357.8 2250.71   367.8 2246.03   397.6 2227.84   400.1 2227.29   407.6 2225.64
   415.1 2225.73   427.1 2226.17   495.6 2233.25   515.1 2236.59   524.9 2236.97
   593.4 2248.73   622.7 2252.64     652 2253.59   730.3 2251.87   828.1 2246.63
#Mann= 3 , 0 , 0
       0      .1       0   400.1    .045       0   415.1      .1       0
Bank Sta=400.1,415.1
XS Rating Curve= 0 ,0
Exp/Cntr=0.3,0.1

Type RM Length L Ch R = 1 ,2294.9  ,525.6,524.2,523
XS GIS Cut Line= 3
     1890366.019      127253.689     1890346.529      126844.653
      1890311.16       126176.33
#Sta/Elev= 30
       0 2277.61    69.9 2271.64   109.9 2264.89   129.8 2263.28   209.7 2252.25
   239.7 2250.92   309.6 2245.45   339.6 2244.39   349.6 2243.02   359.6 2240.14
   399.5 2224.83   402.7  2224.5   409.5  2223.8   417.7 2223.99   529.4 2227.58
   539.4 2228.49   579.3 2236.49   609.3 2239.68   639.2 2239.81   709.2  2233.8
   779.1 2233.15     819 2234.89     859 2238.71     879 2238.84     909 2241.11
   958.9 2247.24  1008.8  2243.9  1048.8 2238.29  1058.8 2237.81  1078.8 2239.43
#Mann= 3 , 0 , 0
       0     .06       0   402.7    .045       0   417.7     .06       0
Bank Sta=402.7,417.7
XS Rating Curve= 0 ,0
Exp/Cntr=0.3,0.1

Type RM Length L Ch R = 1 ,1770.6  ,374.9,373,371
XS GIS Cut Line= 2
     1890912.839      127218.955     1890791.235      126092.839
#Sta/Elev= 30
       0 2316.66    49.7 2305.32    69.6 2301.53    79.5 2301.37    99.4 2297.01
   168.9 2274.21   178.8 2273.39   218.6 2261.44   248.4  2251.1   258.3 2248.76
   268.3 2247.05   317.9 2242.89   357.7 2234.71   377.6 2232.65   418.2 2223.09
   427.2 2222.23   433.2 2222.28   645.8 2224.59   675.6 2225.92   755.1  2246.5
     765 2246.71   784.9 2250.63   854.5    2257   874.3 2257.82   953.8  2266.1
   963.8 2266.26  1033.3 2274.82  1053.2 2278.77    1073 2281.21  1132.7 2295.38
#Mann= 3 , 0 , 0
       0     .06       0   418.2    .045       0   433.2     .06       0
#XS Ineff= 2 , 0
                          541.94         2233.36
Permanent Ineff=
       F       F
Bank Sta=418.2,433.2
XS Rating Curve= 0 ,0
Exp/Cntr=0.3,0.1

Type RM Length L Ch R = 1 ,1397.8  ,423.5,420.1,416.7
XS GIS Cut Line= 3
     1891313.706      127157.406     1891238.229      126754.905
     1891159.486       126353.05
#Sta/Elev= 30
       0 2344.53      10 2343.56    59.9 2323.51    99.9 2308.71   109.9 2308.47
   199.8 2278.57   209.8  2277.8   219.7 2274.91   249.7 2264.99   289.7 2249.72
   299.6 2248.55   309.6 2246.27   339.6  2236.8   359.6 2234.64   389.5 2226.56
   418.9 2222.28   429.5    2222   433.9 2223.04   459.5 2231.38   489.4 2239.09
   509.4 2241.41   549.3 2251.06   559.3 2252.78   599.3 2257.95   609.3 2257.97
   689.2 2267.05   759.1 2269.82   779.1 2269.79     789 2267.56     819 2263.77
#Mann= 3 , 0 , 0
       0     .06       0   418.9    .045       0   433.9     .06       0
Bank Sta=418.9,433.9
XS Rating Curve= 0 ,0
Exp/Cntr=0.3,0.1

Type RM Length L Ch R = 1 ,977.6   ,329,311.2,293.5
XS GIS Cut Line= 3
     1891777.419      127032.619     1891641.198       126646.44
     1891504.976      126260.262
#Sta/Elev= 30
       0 2357.87      20 2348.44    49.9 2337.33    79.9 2331.85   159.8 2303.09
   179.8 2298.75   209.7 2287.94   269.7 2263.24   279.7 2262.36   329.6 2239.48
   369.6 2223.36   408.9 2217.86   409.5 2217.77   423.9 2218.63   469.4 2224.47
   479.4 2228.73   489.4 2230.39   539.3  2263.3   569.3 2281.22   589.3 2290.16
   599.3 2292.57   609.3 2296.93   629.2 2300.32   659.2 2300.46   689.2 2297.82
   699.2 2295.47   759.1 2266.23     789 2257.18     799  2257.3     819 2251.95
#Mann= 3 , 0 , 0
       0      .1       0   408.9    .045       0   423.9      .1       0
Bank Sta=408.9,423.9
XS Rating Curve= 0 ,0
Exp/Cntr=0.3,0.1

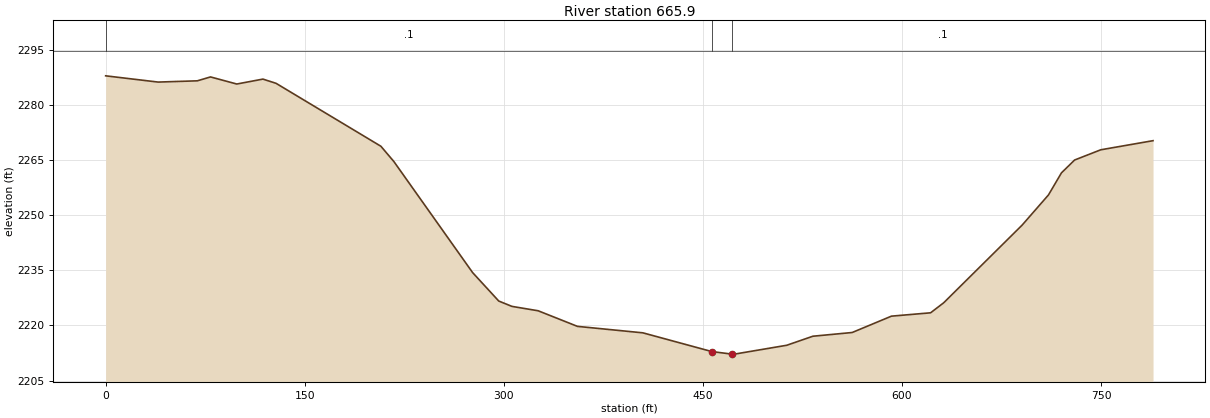
Type RM Length L Ch R = 1 ,665.9   ,669.8,665.4,660.6
XS GIS Cut Line= 3
      1892130.78      126865.149     1891987.113      126539.987
     1891600.237      126343.881
#Sta/Elev= 30
       0 2287.89    39.5 2286.19    69.1 2286.53      79 2287.59    98.8 2285.66
   118.5    2287   128.4 2285.85   207.4 2268.73   217.2 2264.56   276.5 2234.37
   296.2 2226.63   306.1 2225.18   325.9 2223.98   355.5 2219.74   404.8 2217.98
   456.7 2212.89   471.7  2212.2   473.8 2212.19   513.2  2214.6   532.9 2217.06
   562.5 2218.07   592.1 2222.52   621.6 2223.43   631.5 2226.17   690.6  2247.3
   710.4 2255.49   720.2  2261.5   730.1 2264.99   749.8 2267.77   789.2 2270.25
#Mann= 3 , 0 , 0
       0      .1       0   456.7    .045       0   471.7      .1       0
Bank Sta=456.7,471.7
XS Rating Curve= 0 ,0
Exp/Cntr=0.3,0.1

Chan Stop Cuts=-1
Use User Specified Reach Order=0
Composite Channel Slope=5